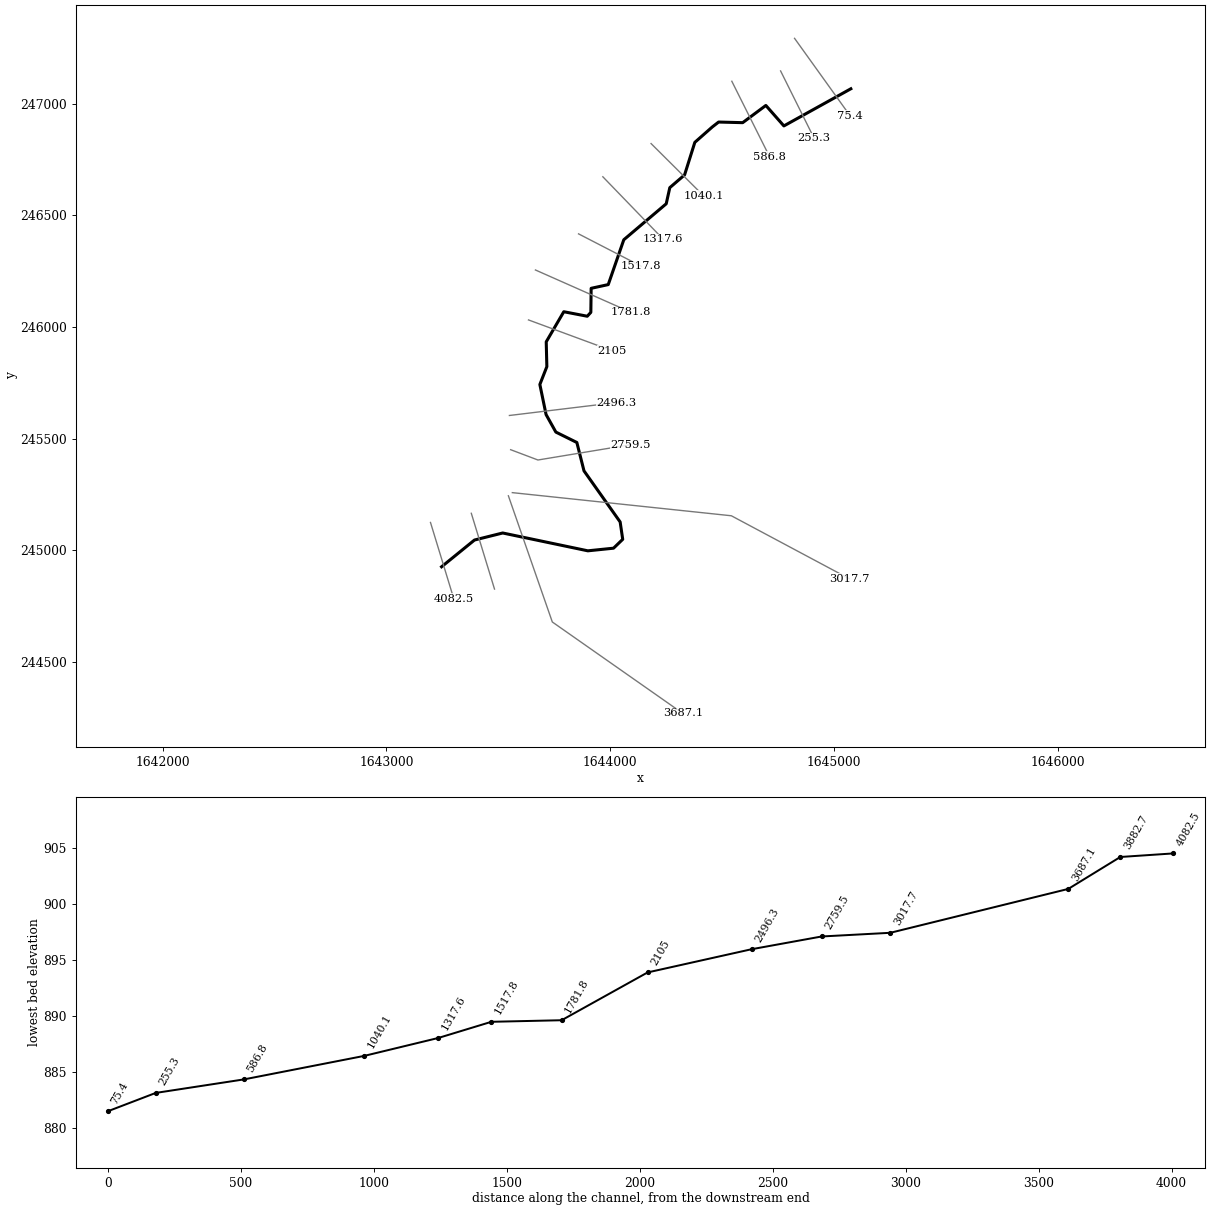
--- LTLINDNFK.prj (project) ---

Proj Title=LTLINDNFK
Current Plan=p01
Geom File=g01
Flow File=f01
Plan File=p01
DSS Export Rating Curves=0
DSS Export Rating Curve Sorted=0
DSS Export Volume Flow Curves=0
DXF OffsetX=0
DXF OffsetY=0
DXF ScaleX=0
DXF ScaleY=0

--- LTLINDNFK.p01 (plan) ---

Plan Title=Floodplain
Program Version=4.00
Geom File=g01
Flow File=f01
K Sum by GR=0
Std Step Tol=0.01
Critical Tol=0.01
Num of Std Step Trials=20
Max Error Tol=0.3
Flow Tol Ratio=0.001
Split Flow NTrial=30
Split Flow Tol=0.02
Split Flow Ratio=0.02
Log Output Level=0
Friction Slope Method=1
Unsteady Friction Slope Method=2
Unsteady Bridges Friction Slope Method=1
Global Log Level=0
CheckData=False
Run HTab=0
Run UNet=0
Run PostProcess=0
UNET Theta=0
UNET Theta Warmup=0
UNET ZTol=0
UNET ZSATol=0
UNET MxIter=0
UNET MaxInSteps=0
UNET DtIC=0
UNET DtMin=0
UNET MaxCRTS=0
UNET WFStab=0
UNET SFStab=0
UNET WFX=0
UNET SFX=0
UNET DSS MLevel=0
UNET DZMax Abort=0
UNET Convert EG Bridges=0
UNET Use Existing IB Tables=0
UNET Froude Limit=0
UNET Froude Power=0
Write IC File=0
Echo Input=False
Echo Output=False
Write Detailed=0

--- LTLINDNFK.f01 (steady flow) ---

Flow Title=NFF Regression Equation
Program Version=4.10
Number of Profiles= 1
Profile Names=P100yr
River Rch & RM=LTLINDNFK,Main            ,4082.5
544.2975
River Rch & RM=LTLINDNFK,Main            ,3687.1
571.4119
River Rch & RM=LTLINDNFK,Main            ,3017.7
848.5266
River Rch & RM=LTLINDNFK,Main            ,3017.7
848.5266
River Rch & RM=LTLINDNFK,Main            ,2759.5
1149.902
River Rch & RM=LTLINDNFK,Main            ,255.3
1187.459
Boundary for River Rch & Prof#=LTLINDNFK,Main            , 1
Up Type= 0
Dn Type= 3
Dn Slope=0.00904
DSS Import GetInterval= 0
DSS Import GetPeak= 0
DSS Import FillOption= 0

--- LTLINDNFK.g01 (geometry) ---

Geom Title=USGS 10m DEM
Program Version=4.10

River Reach=LTLINDNFK       ,Main
Reach XY= 30
     1643246.294      244926.133     1643393.401      245045.921
     1643519.493      245077.444      1643899.87      244997.586
     1644014.681      245009.382     1644055.658      245049.078
     1644044.192      245126.833     1643882.673      245355.559
     1643850.728      245482.643     1643756.978      245529.171
     1643713.228      245607.643      1643685.45      245742.365
       1643716.7      245822.226     1643713.923      245933.338
     1643792.395       246068.06     1643897.256      246047.921
     1643913.228      246065.282     1643914.617      246172.921
     1643991.006      246189.587      1644060.45      246390.282
     1644250.034      246551.393     1644266.006      246623.615
     1644331.978       246680.56     1644377.812      246826.393
     1644455.589      246895.143     1644484.062      246917.365
     1644591.701      246914.588     1644695.173      246991.671
     1644775.728      246900.004      1645074.86       247066.28

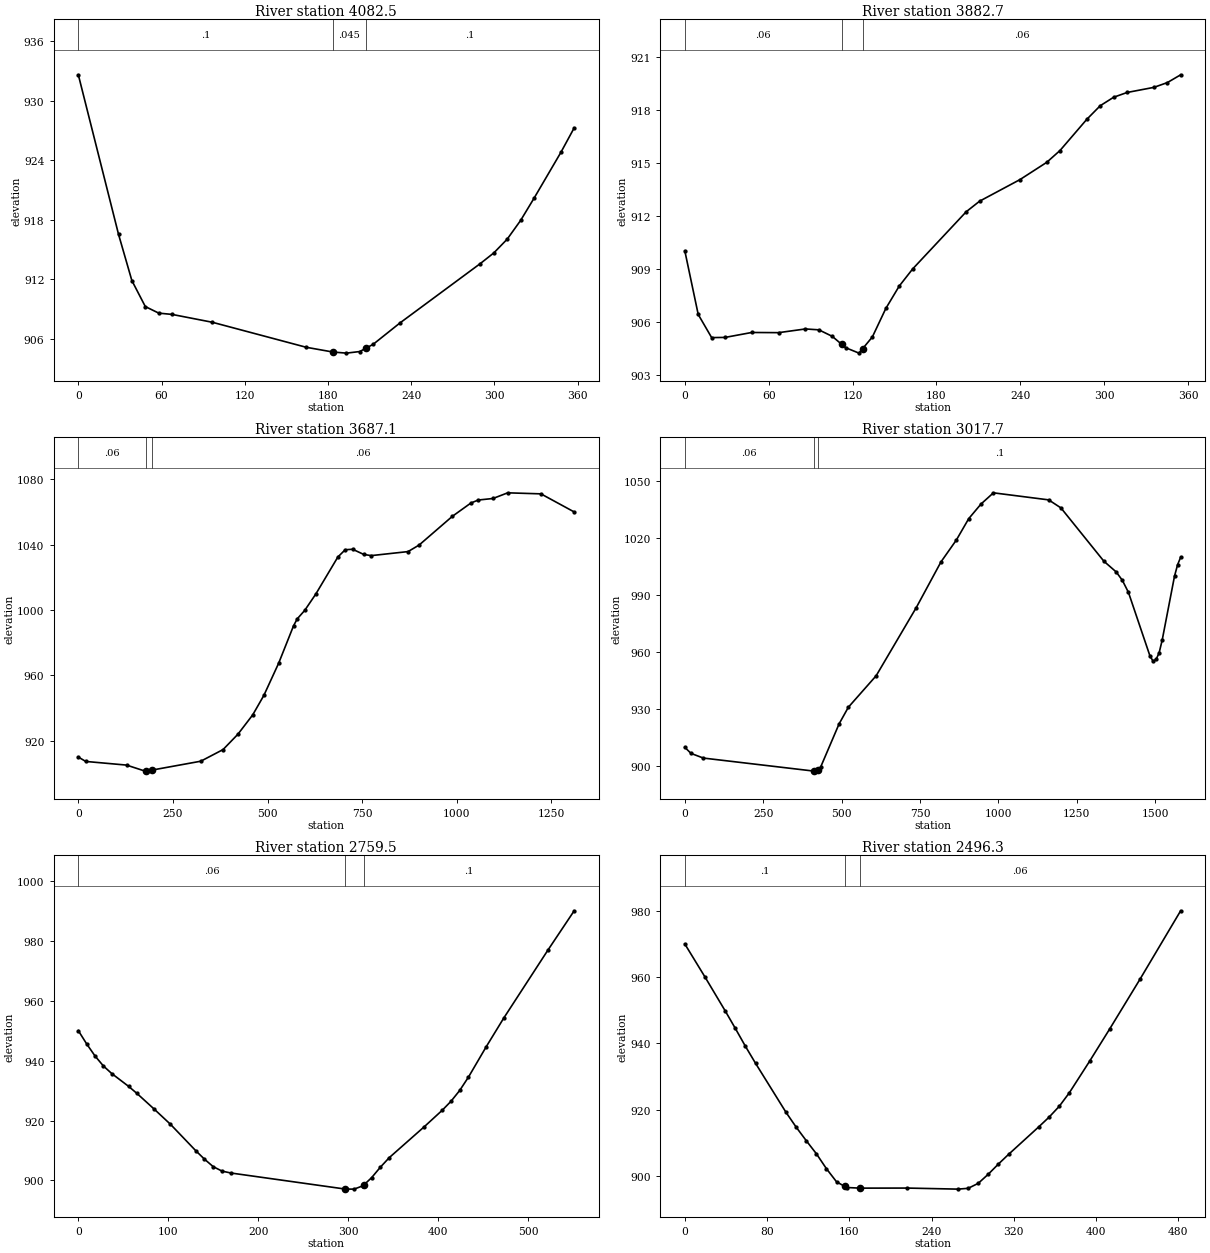
Type RM Length L Ch R = 1 ,4082.5  ,199.3,199.8,200.2
XS GIS Cut Line= 2
     1643196.849      245124.561     1643301.015      244782.547
#Sta/Elev= 21
       0  932.59      29  916.51    38.6  911.86    48.3  909.24      58  908.58
    67.6  908.45    96.6  907.66   164.3  905.14   183.6  904.66   193.3  904.55
   202.9  904.71   207.2  905.03   212.6  905.44   231.9  907.59   289.9  913.58
   299.6  914.65   309.2  916.03   318.9  917.92   328.5  920.14   347.9  924.77
   357.5  927.24
#Mann= 3 , 0 , 0
       0      .1       0   183.6    .045       0   207.2      .1       0
Bank Sta=183.6,207.2
XS Rating Curve= 0 ,0
Exp/Cntr=0.3,0.1

Type RM Length L Ch R = 1 ,3882.7  ,193.7,195.7,196.6
XS GIS Cut Line= 2
     1643379.197      245165.611     1643482.844       244826.35
#Sta/Elev= 29
       0  910.03     9.6  906.42    19.2  905.11    28.8  905.12    47.9   905.4
    67.1  905.39    86.3   905.6    95.9  905.55   105.5  905.18   112.2  904.73
     115  904.54   124.6  904.23   127.2  904.48   134.2  905.15   143.8  906.76
   153.4  908.03     163     909   201.3  912.24   210.9  912.84   239.7  914.06
   258.9  915.04   268.4  915.71   287.6  917.48   297.2  918.25   306.8  918.73
   316.4     919   335.6  919.29   345.2  919.56   354.7     920
#Mann= 3 , 0 , 0
       0     .06       0   112.2    .045       0   127.2     .06       0
Bank Sta=112.2,127.2
XS Rating Curve= 0 ,0
Exp/Cntr=0.3,0.1

Type RM Length L Ch R = 1 ,3687.1  ,642.8,669.4,695.1
XS GIS Cut Line= 3
     1643544.828      245243.979     1643741.107      244678.974
     1644323.895       244269.78
#Sta/Elev= 30
       0  909.97    19.6   907.3   127.5  905.06   176.5  901.37   178.9  901.42
   193.9  901.98   323.6  907.44   382.4  914.56   421.6  923.93   460.8  935.79
   490.3  947.73   529.5  967.49   568.7  990.32   578.5  994.59   598.1   999.7
   627.4 1009.71   685.9 1032.45   705.4 1036.88   724.9 1037.14   754.2 1033.99
   773.7 1033.26   871.3 1035.73   900.5 1039.73   988.3  1057.3  1037.1 1065.41
  1056.6 1067.28  1095.6 1068.22  1134.6 1071.69  1222.4 1071.06  1310.2    1060
#Mann= 3 , 0 , 0
       0     .06       0   178.9    .045       0   193.9     .06       0
Bank Sta=178.9,193.9
XS Rating Curve= 0 ,0
Exp/Cntr=0.3,0.1

Type RM Length L Ch R = 1 ,3017.7  ,250.1,258.2,266.1
XS GIS Cut Line= 3
     1643562.489      245258.084     1644541.014      245154.536
     1645067.321      244873.047
#Sta/Elev= 30
       0     910    19.7  906.78      59  904.32   410.8  897.47   413.3  897.44
   425.8  898.22     433  899.53     492  922.34   521.5  931.08   610.1  947.64
     738  983.52   816.7 1007.55   865.9 1019.11   905.3 1030.35   944.6 1038.06
     984 1043.92  1160.1 1040.21  1199.2 1035.98  1336.2 1007.91  1375.4 1002.28
  1394.9   997.9  1414.5   991.5    1483  958.08  1492.8  955.36  1502.6  956.21
  1512.4  959.77  1522.1  966.47  1561.3 1000.06  1571.1 1006.04  1580.8 1009.98
#Mann= 3 , 0 , 0
       0     .06       0   410.8    .045       0   425.8      .1       0
Bank Sta=410.8,425.8
XS Rating Curve= 0 ,0
Exp/Cntr=0.3,0.1

Type RM Length L Ch R = 1 ,2759.5  ,263.4,263.2,261.9
XS GIS Cut Line= 3
     1643554.967      245450.373     1643676.864      245404.224
     1644091.741       245473.03
#Sta/Elev= 30
       0     950     9.3  945.56    18.6  941.53    27.9   938.2    37.2  935.67
    55.9   931.4    65.2  929.03    83.8  923.95   102.4  918.74   130.3  909.99
   140.1  907.12   149.9   904.6   159.7  903.12   169.5  902.49   296.6  897.13
   306.4  897.11   316.2  898.22   317.6  898.61   325.9  900.95   335.7  904.47
   345.5  907.63   384.6     918   404.2   923.4     414  926.41   423.7  930.03
   433.5  934.52   453.1  944.59   472.6  954.17   521.5  976.78   550.9     990
#Mann= 3 , 0 , 0
       0     .06       0   296.6    .045       0   317.6      .1       0
Bank Sta=296.6,317.6
XS Rating Curve= 0 ,0
Exp/Cntr=0.3,0.1

Type RM Length L Ch R = 1 ,2496.3  ,402.1,391.3,380
XS GIS Cut Line= 2
     1643549.432      245603.544      1644028.18      245661.622
#Sta/Elev= 30
       0     970    19.7  959.99    39.4  949.74    49.2  944.47      59  939.08
    68.9  933.92    98.4  919.18   108.3   914.7   118.1  910.62     128  906.65
   137.8  902.13   147.6  898.18   155.4  896.82   157.5  896.46   170.4  896.27
   216.5  896.29   265.7  895.97   275.6  896.21   285.4  897.71   295.3   900.5
   305.1  903.56   314.9  906.45   344.5  914.83   354.3  917.69   364.2  920.96
     374  925.04   393.7  934.56   413.4  944.38   442.9  959.41   482.3     980
#Mann= 3 , 0 , 0
       0      .1       0   155.4    .045       0   170.4     .06       0
Bank Sta=155.4,170.4
XS Rating Curve= 0 ,0
Exp/Cntr=0.3,0.1

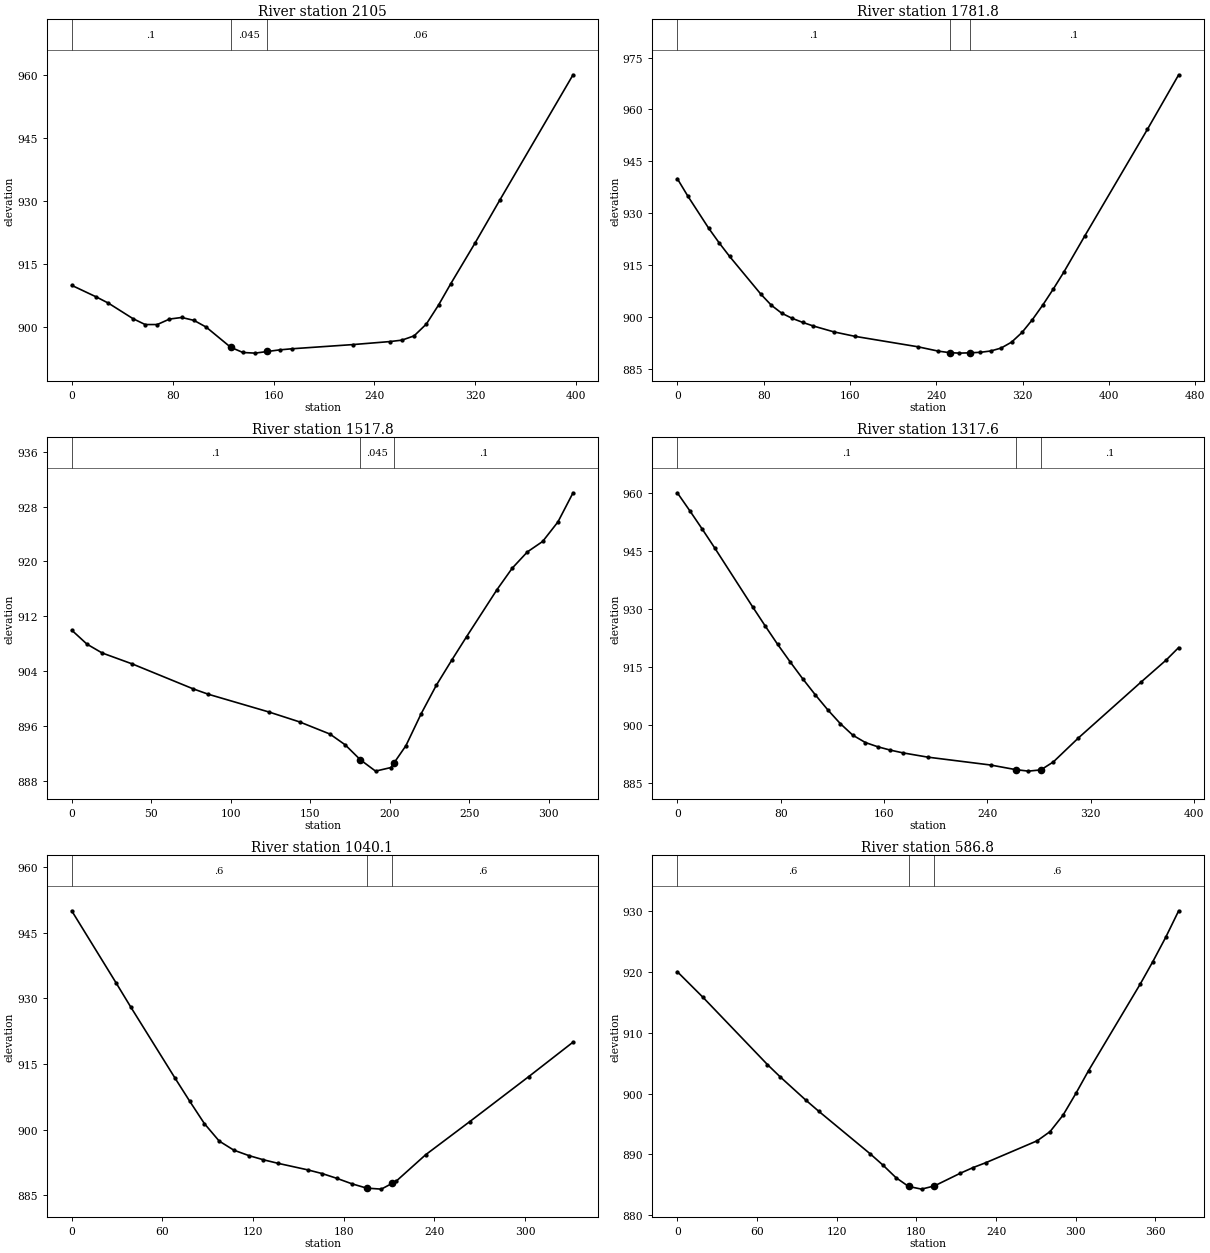
Type RM Length L Ch R = 1 ,2105    ,319.9,323.2,321.6
XS GIS Cut Line= 2
     1643634.724      246031.367     1644007.429       245893.57
#Sta/Elev= 26
       0  909.99    19.4  907.25    29.1  905.76    48.5  902.09    58.2  900.68
    67.8  900.68    77.5  901.98    87.2  902.36    96.9  901.67   106.6  900.07
     126  895.28   135.7  894.04   145.4  893.89   155.1  894.28   164.8  894.66
   174.4  894.92   222.9  895.92     252  896.63   261.7  896.97   271.4  897.99
   281.1  900.79   290.8  905.32   300.4  910.34   319.8  920.08   339.2  930.17
   397.4     960
#Mann= 3 , 0 , 0
       0      .1       0     126    .045       0   155.1     .06       0
Bank Sta=126,155.1
XS Rating Curve= 0 ,0
Exp/Cntr=0.3,0.1

Type RM Length L Ch R = 1 ,1781.8  ,263.4,264,263.8
XS GIS Cut Line= 2
     1643665.689      246254.994     1644090.457      246066.444
#Sta/Elev= 30
       0  939.99     9.7  934.98      29  925.71    38.7  921.49    48.4  917.56
    77.5  906.61    87.1  903.45    96.8  901.13   106.5  899.65   116.2  898.49
   125.9  897.46   145.2  895.74   164.6  894.46   222.7  891.46     242  890.18
   252.4  889.75   261.4  889.61   271.1   889.7   280.8  889.84   290.5  890.23
   300.1  891.07   309.8  892.78   319.5  895.58   329.2  899.31   338.9  903.57
   348.6  908.17   358.2  912.98   377.6  923.42   435.7  954.23   464.7     970
#Mann= 3 , 0 , 0
       0      .1       0   252.4    .045       0   271.1      .1       0
Bank Sta=252.4,271.1
XS Rating Curve= 0 ,0
Exp/Cntr=0.3,0.1

Type RM Length L Ch R = 1 ,1517.8  ,207.3,200.1,192.8
XS GIS Cut Line= 2
     1643858.279      246416.731      1644138.34      246271.851
#Sta/Elev= 25
       0     910     9.6  907.96    19.1  906.68    38.2  905.07    76.4  901.45
      86  900.66   124.2  898.07   143.3  896.64   162.4  894.87     172   893.3
   181.6  891.11   191.1  889.47   200.7  889.99   202.7  890.66   210.2  893.18
   219.8  897.84   229.3  901.97   238.9  905.59   248.4  909.07   267.5  915.91
   277.1  919.04   286.6   921.4   296.2  922.92   305.8  925.76   315.3     930
#Mann= 3 , 0 , 0
       0      .1       0   181.6    .045       0   202.7      .1       0
Bank Sta=181.6,202.7
XS Rating Curve= 0 ,0
Exp/Cntr=0.3,0.1

Type RM Length L Ch R = 1 ,1317.6  ,277.3,277.6,277.6
XS GIS Cut Line= 2
     1643966.893      246672.286     1644236.447       246392.89
#Sta/Elev= 27
       0     960     9.7  955.34    19.4  950.56    29.1  945.66    58.2  930.56
    67.9  925.64    77.6  920.84    87.4  916.26    97.1   911.9   106.8  907.77
   116.5  903.87   126.2  900.31   135.9  897.31   145.6  895.42   155.3  894.31
     165  893.45   174.7  892.74   194.1  891.63   242.6   889.6     262  888.41
   271.8  888.02   281.5  888.34   291.2  890.41   310.6  896.61   359.1  911.06
   378.5  916.74   388.2  919.98
#Mann= 3 , 0 , 0
       0      .1       0     262    .045       0   281.5      .1       0
Bank Sta=262,281.5
XS Rating Curve= 0 ,0
Exp/Cntr=0.3,0.1

Type RM Length L Ch R = 1 ,1040.1  ,460.6,453.3,445.8
XS GIS Cut Line= 2
     1644182.349      246820.999     1644417.338      246586.808
#Sta/Elev= 23
       0     950    29.3  933.57      39  928.06    68.3  911.82    78.1   906.5
    87.8  901.39    97.6   897.4   107.3  895.32   117.1   894.1   126.8  893.13
   136.6  892.31   156.1  890.83   165.9  889.96   175.6  888.87   185.4  887.64
   195.2  886.65   204.9  886.42   212.2  887.76   214.7  888.22   234.2  894.26
   263.5  901.86   302.5  912.13   331.8     920
#Mann= 3 , 0 , 0
       0      .6       0   195.2    .045       0   212.2      .6       0
Bank Sta=195.2,212.2
XS Rating Curve= 0 ,0
Exp/Cntr=0.3,0.1

Type RM Length L Ch R = 1 ,586.8   ,329.1,331.5,331.1
XS GIS Cut Line= 2
     1644543.141      247099.963     1644711.812      246762.241
#Sta/Elev= 24
       0     920    19.4  915.78    67.8  904.77    77.4  902.75    96.8  898.91
   106.5  897.09   145.2  890.11   154.9  888.24   164.6   886.2   174.1  884.75
   183.9  884.31   193.6  884.84     213  886.91   222.6  887.84   232.3  888.65
     271  892.25   280.7  893.76   290.4  896.44   300.1  900.02   309.7  903.78
   348.5  917.95   358.1  921.68   367.8  925.67   377.5     930
#Mann= 3 , 0 , 0
       0      .6       0   174.1    .045       0   193.6      .6       0
Bank Sta=174.1,193.6
XS Rating Curve= 0 ,0
Exp/Cntr=0.3,0.1

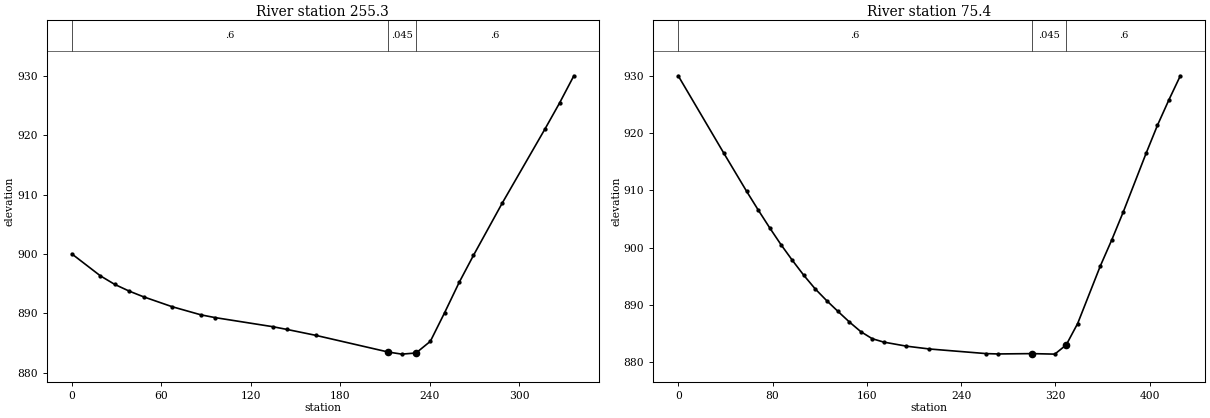
Type RM Length L Ch R = 1 ,255.3   ,175.7,179.9,183.6
XS GIS Cut Line= 2
     1644761.024      247146.259     1644910.727      246844.777
#Sta/Elev= 22
       0     900    19.2  896.29    28.8  894.85    38.5  893.72    48.1  892.76
    67.3  891.09    86.6  889.72    96.2  889.25   134.6  887.73   144.3  887.26
   163.5  886.27   212.2  883.45   221.2   883.1   230.8  883.29   240.4  885.26
     250   890.1   259.7  895.18   269.3  899.74   288.5  908.51   317.4  921.11
     327  925.41   336.6     930
#Mann= 3 , 0 , 0
       0      .6       0   212.2    .045       0   230.8      .6       0
Bank Sta=212.2,230.8
XS Rating Curve= 0 ,0
Exp/Cntr=0.3,0.1

Type RM Length L Ch R = 1 ,75.4    ,68.9,75.4,82.3
XS GIS Cut Line= 2
     1644823.383      247292.155      1645071.36      246945.755
#Sta/Elev= 30
       0     930    38.7   916.5    58.1  909.83    67.8  906.62    77.5  903.52
    87.1  900.58    96.8  897.83   106.5  895.22   116.2  892.84   125.9   890.8
   135.6   888.9   145.2  887.07   154.9  885.38   164.6  884.15   174.3  883.56
   193.6  882.85     213  882.36   261.4  881.55   271.1  881.49   300.1  881.55
   319.5  881.46   329.2  883.07   338.9   886.8   358.2  896.87   367.9  901.41
   377.6  906.26     397   916.5   406.6  921.37   416.3   925.8     426     930
#Mann= 3 , 0 , 0
       0      .6       0   300.1    .045       0   329.2      .6       0
Bank Sta=300.1,329.2
XS Rating Curve= 0 ,0
Exp/Cntr=0.3,0.1

Chan Stop Cuts=-1
Use User Specified Reach Order=0
Composite Channel Slope=5